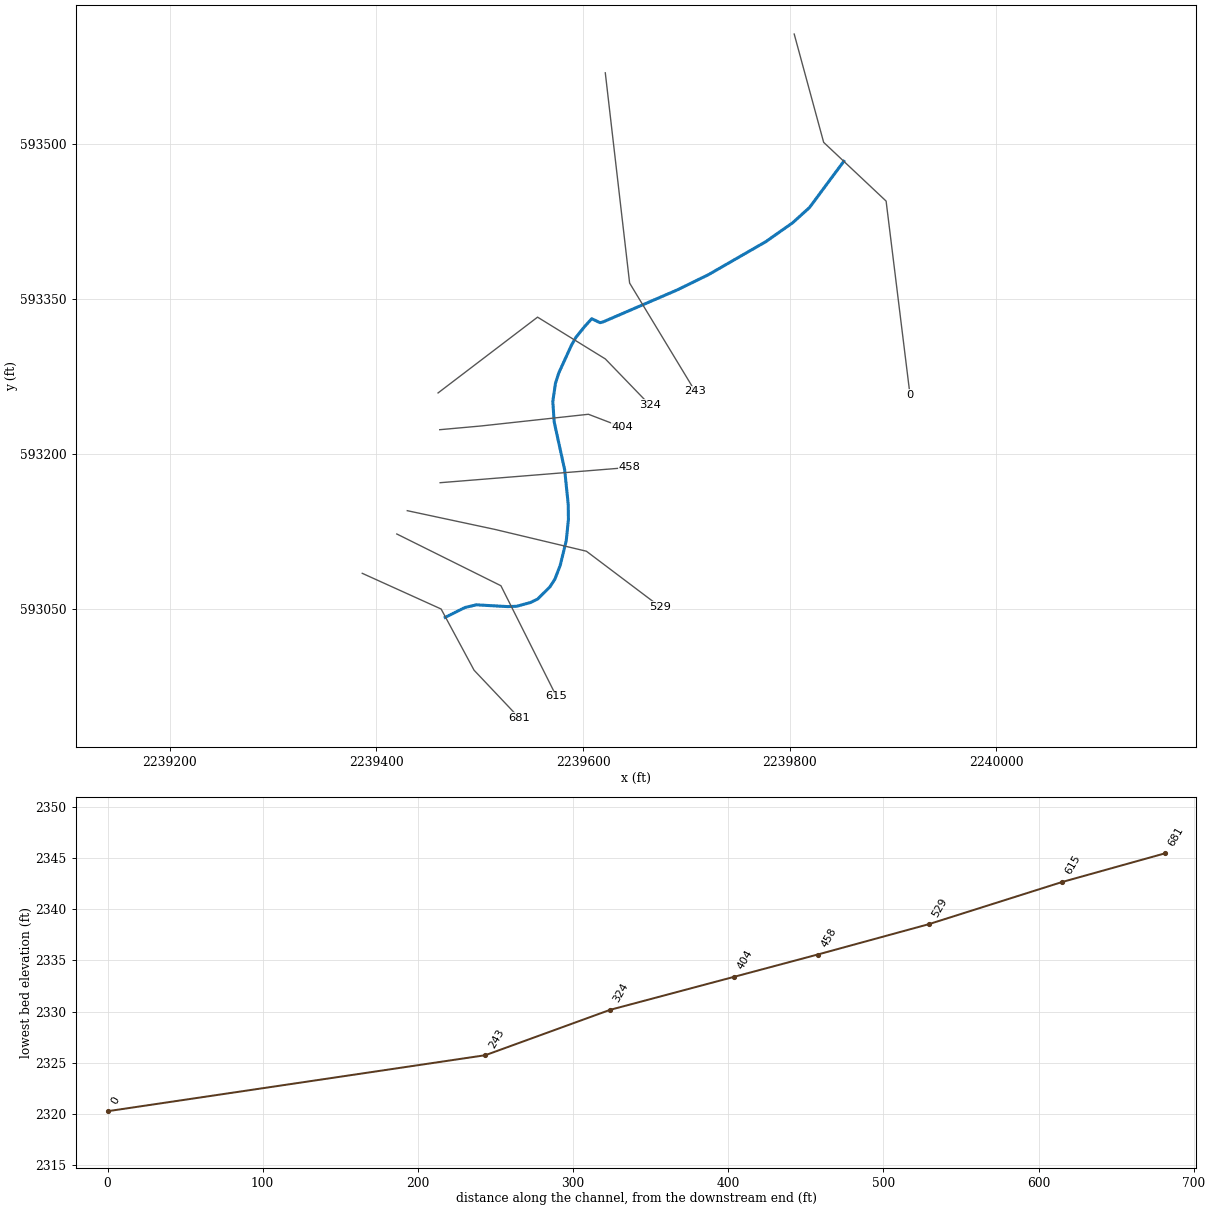
--- CLAYRNT1.prj (project) ---

Proj Title=CLAYRNT1
Current Plan=p01
Default Exp/Contr=0,0
English Units
Geom File=g01
Flow File=f01
Plan File=p01
BEGIN DESCRIPTION:
----------MODEL BY WOOD PLC 2022----------
AFH study
Randolph County, WV
HEC-RAS Version: RAS 6.2
Vertical Datum: NAVD88
Projection: NAD 1983 StatePlane West Virginia S FIPS 4702 (US Feet)
Terrain: 1-meter LIDAR (FEMA Region III 3DEP collected 2016-2018)
Land Use: 2019 NLCD
Hydrologic Method:
WV SIR2010-5033 regression equations
Additional Model Notes:
KWSE coincident peak with Clay Run
END DESCRIPTION:
DSS Export Rating Curves= 0
DSS Export Rating Curve Sorted= 0
DSS Export Volume Flow Curves= 0
DXF OffsetX= 0
DXF OffsetY= 0
DXF ScaleX= 0
DXF ScaleY= 0

--- CLAYRNT1.p01 (plan) ---

Plan Title=Floodplain
Program Version=6.20
Short Identifier=Floodplain
Geom File=g01
Flow File=f01
Subcritical Flow
K Sum by GR= 0
Std Step Tol= 0.01
Critical Tol= 0.01
Num of Std Step Trials= 20
Max Error Tol= 0.3
Flow Tol Ratio= 0.001
Split Flow NTrial= 30
Split Flow Tol= 0.02
Split Flow Ratio= 0.02
Log Output Level= 0
Friction Slope Method= 1
Unsteady Friction Slope Method= 2
Unsteady Bridges Friction Slope Method= 1
Parabolic Critical Depth
Global Vel Dist= 0 , 0 , 0
Global Log Level= 0
CheckData=True
Encroach Param=-1 ,0,0, 0
Mapping Interval=1HOUR
Computation Time Step Use Courant=        0
Computation Time Step Use Time Series=    0
Computation Time Step Count To Double=0
Computation Time Step Max Doubling=0
Computation Time Step Max Halving=0
Computation Time Step Residence Courant=0
Run HTab= 0
Run UNet= 0
Run Sediment= 0
Run PostProcess= 0
Run WQNet= 0
Run RASMapper=-1
UNET Theta= 0
UNET Theta Warmup= 0
UNET ZTol= 0
UNET ZSATol= 0
UNET MxIter= 0
UNET Max Iter WO Improvement= 0
UNET MaxInSteps= 0
UNET DtIC= 0
UNET DtMin= 0
UNET MaxCRTS= 0
UNET WFStab= 0
UNET SFStab= 0
UNET WFX= 1
UNET SFX= 1
UNET Gravity=32.174
UNET 1D Methodology=Finite Difference
UNET DSS MLevel= 1
UNET Pardiso=0
UNET DZMax Abort= 0
UNET Use Existing IB Tables= 0
UNET Froude Reduction=False
UNET Froude Limit= 0
UNET Froude Power= 0
UNET D1 Cores= 0
UNET WindReference=Eulerian
UNET WindDragFormulation=Hsu (1988)
UNET D2 Coriolis=0
UNET D2 Cores= 0
UNET D2 Theta= 1
UNET D2 Theta Warmup= 1
UNET D2 Z Tol= 0.01
UNET D2 Volume Tol= 0.01
UNET D2 Max Iterations= 20
UNET D2 Equation= 0
UNET D2 RampUpFraction=0.1
UNET D2 TimeSlices= 1
UNET D2 Turbulence Formulation=Non-Conservative (original)
UNET D2 Eddy Viscosity=0.3
UNET D2 Transverse Eddy Viscosity=0.1
UNET D2 Smagorinsky Mixing=0
UNET D2 BCVolumeCheck=0
UNET D2 Cores=0
UNET D2 SolverType=PARDISO (Direct)
UNET D2 Minimum Iterations= 2147483647
UNET D2 Maximum Iterations= 2147483647
UNET D2 Restart Number= 10
UNET D2 Relaxation Coeff=1.3
UNET D2 SOR Precondition Iterations= 10
UNET D2 ILUT Maximum Fill= 8
UNET D2 ILUT Tolerance=1E-08
UNET D1D2 MaxIter= 0
UNET D1D2 ZTol=0.01
UNET D1D2 QTol=0.1
UNET D1D2 MinQTol=1
Write IC File= 0
Write IC File at Fixed DateTime=0
Write IC File at Sim End=0
Echo Input=False
Echo Parameters=False
Echo Output=False
Write Detailed= 0
HDF Write Warmup=0
HDF Write Time Slices=0
HDF Flush=0
HDF Compression= 1
HDF Chunk Size= 1
HDF Spatial Parts= 1
HDF Use Max Rows=0
HDF Fixed Rows= 1
Calibration Method= 0
Calibration Iterations= 20
Calibration Max Change=0.05
Calibration Tolerance=0.2
Calibration Maximum=1.5
Calibration Minimum=0.5
Calibration Optimization Method= 1
WQ AD Non Conservative
WQ ULTIMATE=-1
WQ Max Comp Step=1HOUR
WQ Output Interval=15MIN
WQ Output Selected Increments= 0
WQ Output face flow=0
WQ Output face velocity=0
WQ Output face area=0
WQ Output face dispersion=0
WQ Output cell volume=0
WQ Output cell surface area=0
WQ Output cell continuity=0
WQ Output cumulative cell continuity=0
WQ Output face conc=0
WQ Output face dconc_dx=0
WQ Output face courant=0
WQ Output face peclet=0
WQ Output face adv mass=0
WQ Output face disp mass=0
WQ Output cell mass=0
WQ Output cell source sink temp=0
WQ Output nsm pathways=0
WQ Output nsm derived pathways=0
WQ Create Restart=0
WQ Fixed Restart=0
WQ System Summary=0
WQ Write To DSS=0
Sorting and Armoring Iterations= 10
XS Update Threshold= 0.02
Bed Roughness Predictor= 0
Hydraulics Update Threshold= 0.02
Energy Slope Method= 1
Volume Change Method= 1
Sediment Retention Method= 0
Sediment TS Multiplier= 1
Warm Up Method= 0
XS Weighting Method= 0
Number of US Weighted Cross Sections= 1
Number of DS Weighted Cross Sections= 1
Upstream XS Weight=0
Main XS Weight=1
Downstream XS Weight=0
Number of DS XS's Weighted with US Boundary= 1
Upstream Boundary Weight= 1
Weight of XSs Associated with US Boundary= 0
Number of US XS's Weighted with DS Boundary= 1
Downstream Boundary Weight= 0.5
Weight of XSs Associated with DS Boundary= 0.5
Percentile Method= 0
Sediment Output Level= 3
Mass or Volume Output= 0
Output Increment Type= 1
Profile and TS Output Increment= 1
Transport Output Increment 1
XS Output Flag= 0
XS Output Increment= 10
Read HDF5 Sediment Hotstart= 0
Sediment Hotstart Type= 0
Write Gradation File= 0
Read Gradation Hotstart= 0
Write HDF5 File= 1
Write Binary Output= 1
Write DSS Sediment File= 0
DSS Sediment Output Type= 1
SV Curve= 0
Specific Gage Flag= 0
Subcell Erosion Methods= 0
Subcell Deposition Methods= 0
Advection Scheme= 1
Matrix Solver= 0
Implicit Weighting Factor= 1
Maximum Outer Loop Convergence Iterations= 5
Convergence Maximum Absolute= 0.001
Convergence RMSE= 0.0001
Grain Fractions Max Abs Error= 0.001
Max Subgrid Regions= 1
Max Subgrid Length Scale= 3.402823E+38
Initial Layer Thickness= 3.402823E+38
Min Layer Thickness= 3.402823E+38
Max Layer Thickness= 3.402823E+38
Number of Layers= 5

--- CLAYRNT1.f01 (steady flow) ---

Flow Title=Flow
Program Version=6.20
Number of Profiles= 1
Profile Names=P100yr
River Rch & RM=CLAYRNT1,Main            ,681
     298
River Rch & RM=CLAYRNT1,Main            ,243
     630
Boundary for River Rch & Prof#=CLAYRNT1,Main            , 1
Up Type= 0
Dn Type= 1
Dn Known WS=2322.9
DSS Import GetInterval= 0
DSS Import GetPeak= 0
DSS Import FillOption= 0

--- CLAYRNT1.g01 (geometry) ---

Geom Title=Geometry
Program Version=6.20

River Reach=CLAYRNT1        ,Main
Reach XY= 30
2239466.52100001593042.2099999932239485.61800005593051.759000018
2239496.72900003 593054.363000022239527.11100002593052.627000004
2239535.79200003593052.9740000222239549.16000004593056.620000005
2239555.93000005      593059.9192239567.73600003593071.550000012
2239572.59700003593079.0160000032239577.80500001593092.384000003
2239583.70800003593116.5160000182239585.79099998593137.002000004
     2239585.618593151.412000015     2239582.146593185.091999993
2239571.98000002593231.5540000052239570.68699999593251.238000005
2239573.26000004593268.8610000162239576.54700002593278.944000006
2239588.65000001593305.4790000172239593.06400003593313.225000009
2239601.47400004593323.6560000182239608.32048467593331.227572083
2239616.44500004593327.419000015     2239619.391593328.185000002
     2239691.197      593359.153     2239721.319      593373.878
     2239776.745      593405.778     2239802.759      593424.076
      2239819.09      593438.8282239852.29352219593483.608799487

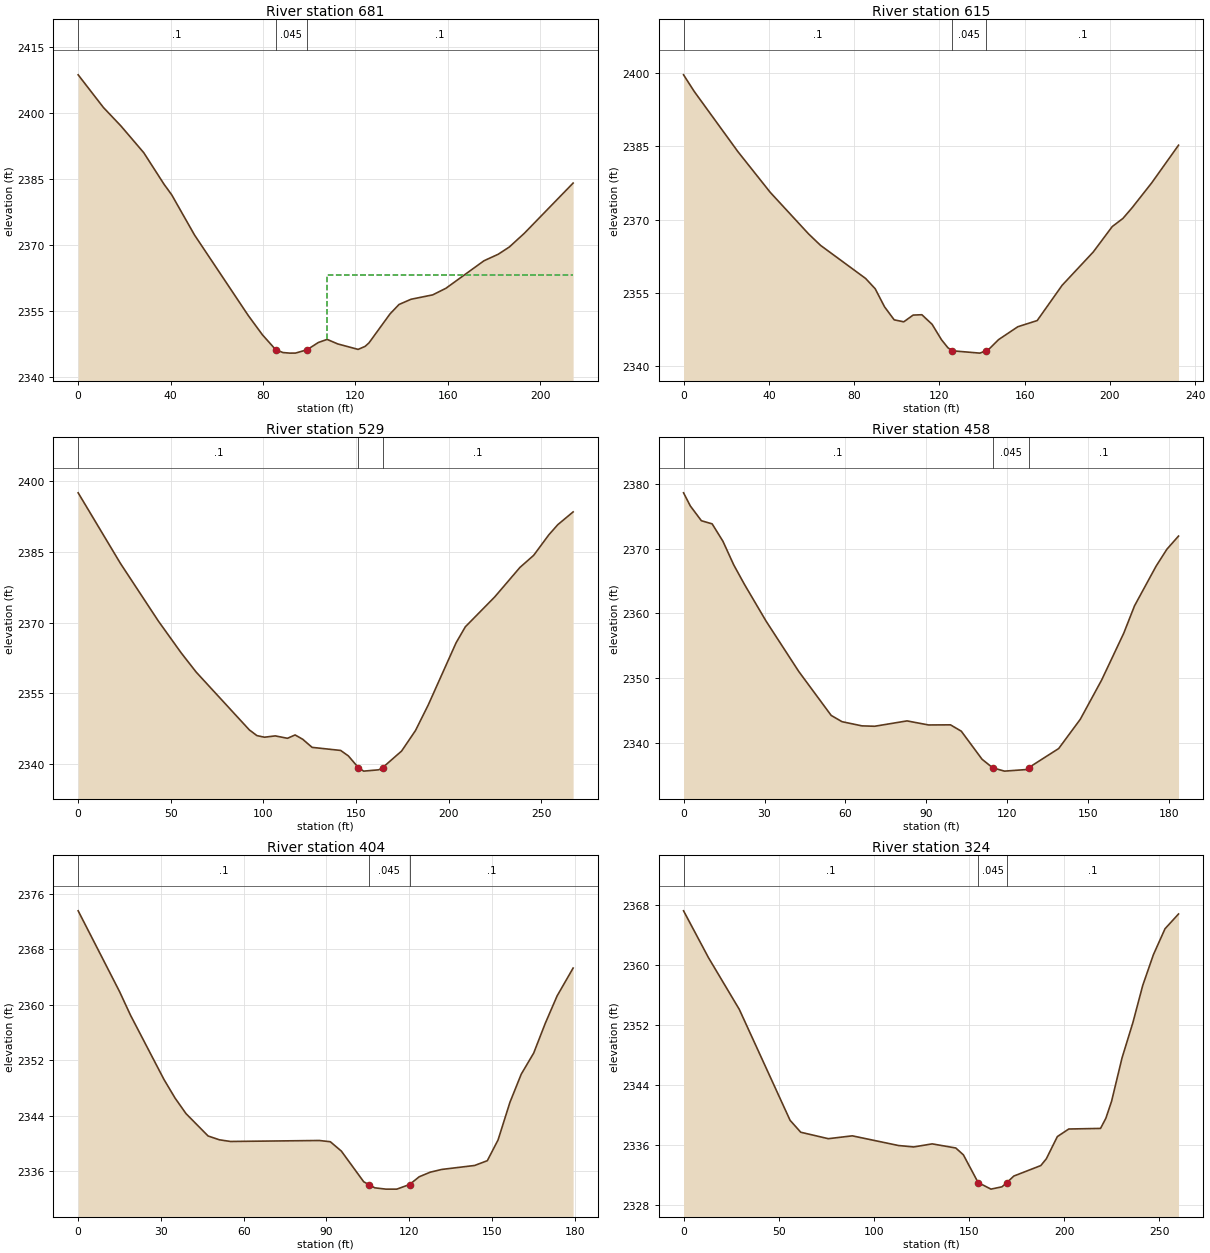
Type RM Length L Ch R = 1 ,681     ,66.3,66.3,66.3
XS GIS Cut Line= 4
2239386.26947064593084.847360517 2239462.5815865593050.306087023
2239494.49167749592991.0623429192239537.94379002592945.157081346
#Sta/Elev= 30
       0 2408.74    10.9 2401.34    18.6 2397.07    28.4 2391.04    37.2 2383.86
    40.5 2381.47    50.4 2372.32    73.7    2354    79.8 2349.64   85.562346.253
    88.7 2345.62    91.7 2345.49    94.1  2345.5   99.092346.254     104 2347.91
   107.8 2348.61   112.4 2347.58   121.2 2346.34   124.2 2347.01   125.9 2347.81
     135 2354.39   138.9 2356.54   144.1 2357.73   153.5 2358.73   159.2 2360.22
   175.7 2366.48   181.9 2367.97   186.7 2369.62   193.2 2372.74   214.3 2384.14
#Mann= 3, -1 ,  0
       0     0.1       0   85.56   0.045       0   99.09     0.1       0
#XS Ineff= 2 , 0
                          107.76         2363.17
Permanent Ineff=
       F       F
Bank Sta=85.56,99.09
XS Rating Curve= 0 ,0
Exp/Cntr(USF)=0,0
Exp/Cntr=0.3,0.1

Type RM Length L Ch R = 1 ,615     ,85.9,85.9,85.9
XS GIS Cut Line= 4
2239419.69079537593122.9260459092239520.44113712593072.851347335
2239535.31524612593043.2519767972239574.10924032592965.904954409
#Sta/Elev= 30
       0 2399.66       5 2396.26    25.5 2383.93    40.7 2375.58    58.6 2367.11
    64.3 2364.73    85.4 2357.97    89.9 2355.86    94.3 2352.15    98.8  2349.5
   103.3 2349.09   107.7 2350.47   111.8 2350.54   116.6 2348.58     121 2345.42
     124 2343.79  126.012343.161     139 2342.68   141.9 2343.15   143.5 2343.59
   147.8 2345.45   156.8 2348.08   165.9 2349.35   177.6 2356.57   192.2 2363.39
   201.1 2368.59   206.1 2370.25   210.4 2372.43   219.6 2377.53   232.2 2385.25
#Mann= 3, -1 ,  0
       0     0.1       0  126.01   0.045       0   141.9     0.1       0
Bank Sta=126.01,141.9
XS Rating Curve= 0 ,0
Exp/Cntr(USF)=0,0
Exp/Cntr=0.3,0.1

Type RM Length L Ch R = 1 ,529     ,71.5,71.5,71.5
XS GIS Cut Line= 4
2239429.84332513593145.4731212792239514.75461152593127.319673844
2239603.17946838593106.2382510162239674.62206797 593052.36350379
#Sta/Elev= 30
       0 2397.47    22.8 2382.54    43.3 2370.32    55.6 2363.59    63.7 2359.52
    92.4 2347.28    96.5 2346.07   100.6 2345.73   106.4 2346.01     113  2345.5
   117.1 2346.21   121.2  2345.3   126.3 2343.58   141.7 2342.93   145.9 2341.76
  151.252339.302   154.1 2338.55   162.3 2338.83   164.42339.303   174.6  2342.8
   182.1 2347.14     189 2352.57     204 2365.71     209  2369.1   224.9 2375.44
   238.5 2381.68   245.9 2384.24   254.1 2388.59   258.9 2390.72   267.2 2393.43
#Mann= 3, -1 ,  0
       0     0.1       0  151.25   0.045       0   164.4     0.1       0
Bank Sta=151.25,164.4
XS Rating Curve= 0 ,0
Exp/Cntr(USF)=0,0
Exp/Cntr=0.3,0.1

Type RM Length L Ch R = 1 ,458     ,54,54,54
XS GIS Cut Line= 2
2239461.63977062593172.546793023 2239644.4584989593187.300585129
#Sta/Elev= 30
       0 2378.69     2.5 2376.66     6.6 2374.37    10.6 2373.88    14.6 2371.18
    18.6 2367.52    22.6 2364.48    30.6  2358.8    42.7 2351.01    54.7 2344.21
    58.7 2343.24    66.1 2342.59    70.8 2342.53    82.8 2343.36    90.8 2342.73
    98.9 2342.75   102.9 2341.77   110.6 2337.42  114.552336.094   118.9 2335.58
   126.9 2335.82  127.912336.121     139 2339.08     147 2343.61   154.9 2349.68
   163.1 2356.94   167.1 2361.19   175.1 2367.34   179.1 2369.96   183.4 2371.99
#Mann= 3, -1 ,  0
       0     0.1       0  114.55   0.045       0  127.91     0.1       0
Bank Sta=114.55,127.91
XS Rating Curve= 0 ,0
Exp/Cntr(USF)=0,0
Exp/Cntr=0.3,0.1

Type RM Length L Ch R = 1 ,404     ,79.8,79.8,79.8
XS GIS Cut Line= 4
2239461.24513595593223.8462122252239500.84260568593227.413198871
2239605.14313203593238.7774103362239637.59408203593226.335814208
#Sta/Elev= 30
       0 2373.51      15 2361.87      19 2358.44    31.1  2349.2    35.1 2346.53
    39.1 2344.27    47.1 2341.05    51.2  2340.5    55.2 2340.26    87.4  2340.4
    91.4 2340.22    95.4 2338.87   103.5 2334.45  105.34 2334.05   107.5 2333.58
   111.5 2333.39   115.5 2333.39  120.122334.056   123.6 2335.17   127.6 2335.83
   131.8 2336.23   143.7  2336.8   148.3 2337.49   152.2 2340.49   156.5 2345.91
   160.6 2349.97   165.1    2353   169.3 2357.29   173.6 2361.25   179.4 2365.26
#Mann= 3, -1 ,  0
       0     0.1       0  105.34   0.045       0  120.12     0.1       0
Bank Sta=105.34,120.12
XS Rating Curve= 0 ,0
Exp/Cntr(USF)=0,0
Exp/Cntr=0.3,0.1

Type RM Length L Ch R = 1 ,324     ,80.3,80.3,80.3
XS GIS Cut Line= 4
2239459.62327669593259.4220417522239555.92032386 593332.76937962
2239621.51561193 593292.331450062239664.62177773593247.679836282
#Sta/Elev= 30
       0 2367.24    13.1    2361    29.3 2354.11      56 2339.33    61.6 2337.74
    76.1 2336.88    88.7 2337.26     113 2335.97     121 2335.78   130.7 2336.19
   143.1 2335.64   147.1 2334.73  154.852331.039   161.6 2330.16   167.4 2330.47
  170.01 2331.04   173.6  2331.9   187.8  2333.3   190.7  2334.2   196.5 2337.16
   202.5 2338.17   219.2 2338.25     222  2339.6     225 2341.86   230.5 2347.64
   236.2 2352.34   241.4 2357.31     247  2361.4   253.1 2364.85   260.2 2366.82
#Mann= 3, -1 ,  0
       0     0.1       0  154.85   0.045       0  170.01     0.1       0
Bank Sta=154.85,170.01
XS Rating Curve= 0 ,0
Exp/Cntr(USF)=0,0
Exp/Cntr=0.3,0.1

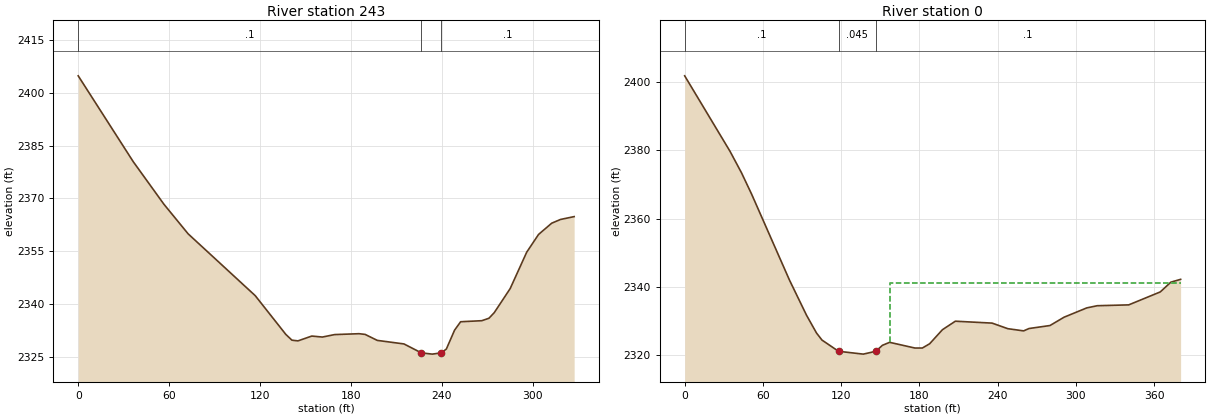
Type RM Length L Ch R = 1 ,243     ,243.5,243.5,243.5
XS GIS Cut Line= 3
2239621.47071153 593569.23134304 2239645.0178215 593365.75383201
2239708.37228123593261.114599803
#Sta/Elev= 30
       0 2404.89    36.3 2380.47    56.6 2368.33    72.5 2359.95   116.8 2342.35
     137 2331.32     141 2329.69     145 2329.49   154.1 2330.86   161.1 2330.58
   169.2 2331.28   185.3 2331.53   189.3 2331.33   197.3 2329.63   214.9 2328.62
   226.4 2326.08   233.6 2325.72   239.6 2326.09   242.9 2327.18   248.3 2332.53
   252.3 2334.93   266.3 2335.23     271 2335.93   274.5 2337.53     285 2344.37
   295.9 2354.72   303.7 2359.76   312.4 2362.97   318.2 2364.03   327.2 2364.84
#Mann= 3, -1 ,  0
       0     0.1       0   226.4   0.045       0   239.6     0.1       0
Bank Sta=226.4,239.6
XS Rating Curve= 0 ,0
Exp/Cntr=0.3,0.1

Type RM Length L Ch R = 1 ,0       ,235.2,235.2,235.2
XS GIS Cut Line= 4
2239804.29509592593606.7527707722239832.80193572593501.939117285
2239893.24183211593445.1001056792239916.35366166593257.704800445
#Sta/Elev= 30
       0 2401.88    34.8 2379.72    43.6 2373.42    51.4 2367.12    80.4 2341.94
    93.5 2331.61   101.1 2326.44   105.3 2324.36  117.992321.063     137 2320.23
  146.572321.063   151.7 2322.82   157.2 2323.69   176.6 2322.02   182.3 2322.02
   187.9 2323.27   197.7 2327.39   207.6 2329.89   235.8 2329.33   247.9 2327.69
     260 2327.05   264.1 2327.74   280.2 2328.62     291 2331.06   308.4 2333.79
   316.4 2334.43   340.6 2334.68   364.8 2338.48   372.9 2341.34   380.4 2342.17
#Mann= 3, -1 ,  0
       0     0.1       0  117.99   0.045       0  146.57     0.1       0
#XS Ineff= 2 , 0
                           157.4         2341.21
Permanent Ineff=
       F       F
Bank Sta=117.99,146.57
XS Rating Curve= 0 ,0
Exp/Cntr=0.3,0.1
LCMann Table=0

Chan Stop Cuts=-1
Use User Specified Reach Order=0
Composite Channel Slope=5